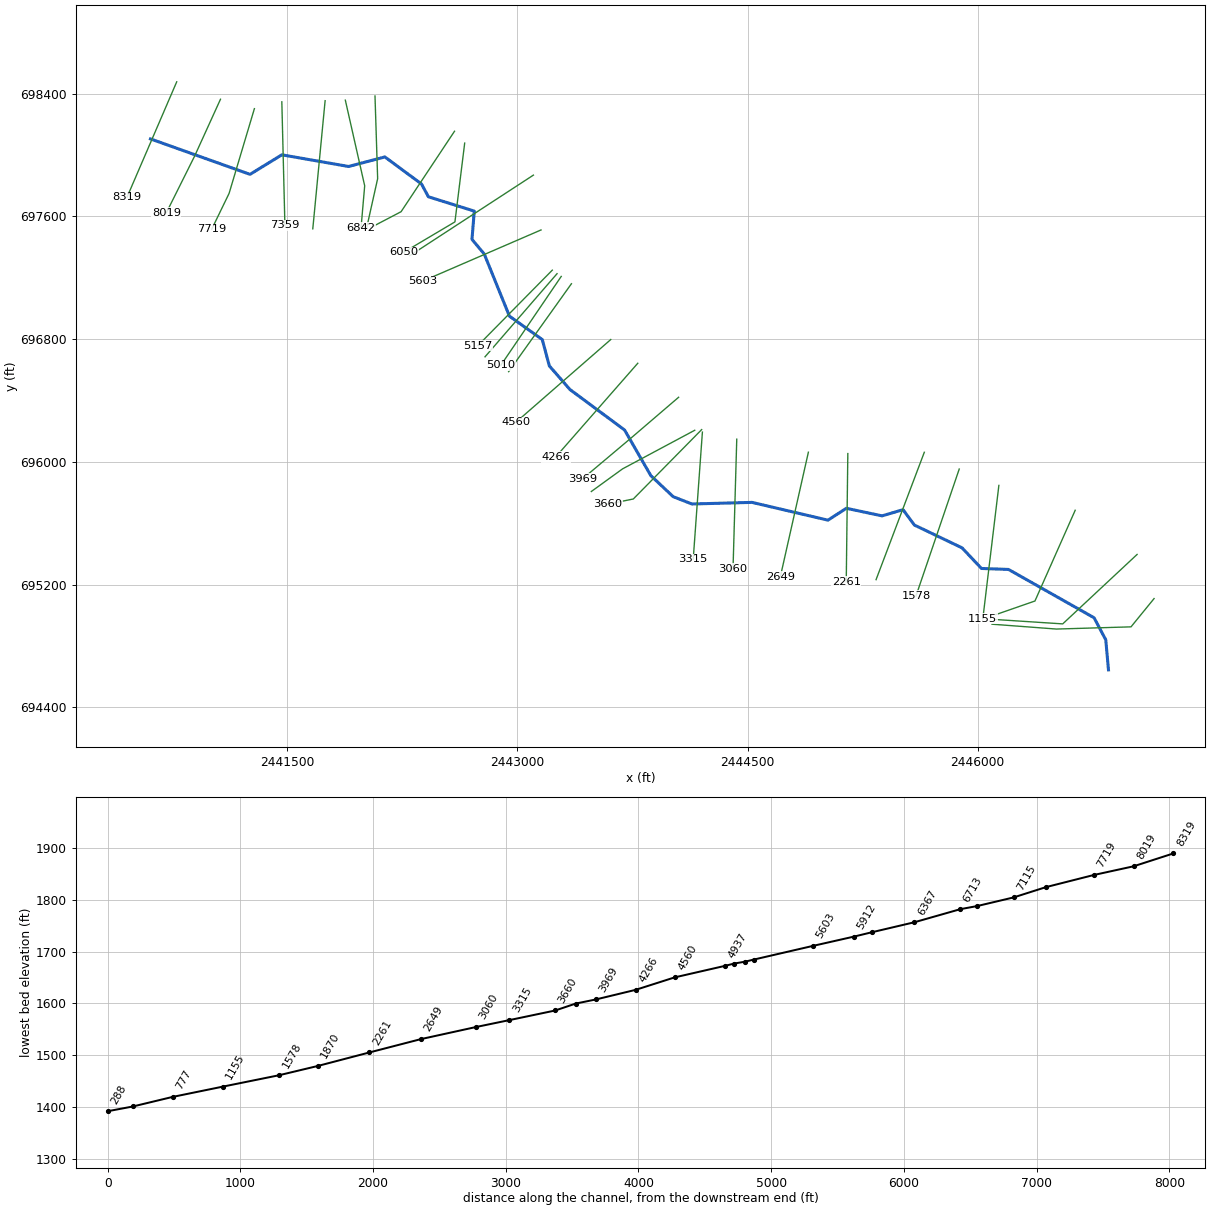
--- SHAFTRN.prj (project) ---

Proj Title=SHAFTRN
Current Plan=p01
Default Exp/Contr=0,0
English Units
Geom File=g01
Flow File=f01
Plan File=p01
BEGIN DESCRIPTION:
Stream Name: Shafter Run
Flood Zone: Approximate
Pendleton County, West Virginia
HEC-RAS Version: 5.0.7
Hydrology Method:
Regression equation
END DESCRIPTION:
DSS File=dss
DSS Export Rating Curves= 0
DSS Export Rating Curve Sorted= 0
DSS Export Volume Flow Curves= 0
DXF OffsetX= 0
DXF OffsetY= 0
DXF ScaleX= 0
DXF ScaleY= 0

--- SHAFTRN.p01 (plan) ---

Plan Title=Floodplain
Program Version=5.07
Short Identifier=Floodplain
Geom File=g01
Flow File=f01
Subcritical Flow
K Sum by GR= 0
Std Step Tol= 0.01
Critical Tol= 0.01
Num of Std Step Trials= 20
Max Error Tol= 0.3
Flow Tol Ratio= 0.001
Split Flow NTrial= 30
Split Flow Tol= 0.02
Split Flow Ratio= 0.02
Log Output Level= 0
Friction Slope Method= 1
Unsteady Friction Slope Method= 2
Unsteady Bridges Friction Slope Method= 1
Parabolic Critical Depth
Global Vel Dist= 0 , 0 , 0
Global Log Level= 0
CheckData=True
Encroach Param=-1 ,0,0, 0
Computation Interval=0.1SEC
Output Interval=1MIN
Instantaneous Interval=Max Profile
Mapping Interval=1HOUR
Computation Time Step Use Courant=        0
Computation Time Step Use Time Series=    0
Computation Time Step Count To Double=0
Computation Time Step Max Doubling=0
Computation Time Step Max Halving=0
Computation Time Step Residence Courant=0
Run HTab= 0
Run UNet= 0
Run Sediment= 0
Run PostProcess= 0
Run WQNet= 0
Run RASMapper=-1
UNET Theta= 0
UNET Theta Warmup= 0
UNET ZTol= 0
UNET ZSATol= 0
UNET MxIter= 0
UNET Max Iter WO Improvement= 0
UNET MaxInSteps= 0
UNET DtIC= 0
UNET DtMin= 0
UNET MaxCRTS= 0
UNET WFStab= 0
UNET SFStab= 0
UNET WFX= 1
UNET SFX= 1
UNET 1D Methodology=Finite Difference
UNET DSS MLevel= 1
UNET Pardiso=0
UNET DZMax Abort= 0
UNET Use Existing IB Tables= 0
UNET Froude Reduction=False
UNET Froude Limit= 0
UNET Froude Power= 0
UNET D1 Cores= 0
UNET D2 Coriolis=0
UNET D2 Cores= 0
UNET D2 Theta= 1
UNET D2 Theta Warmup= 1
UNET D2 Z Tol= 0.01
UNET D2 Volume Tol= 0.01
UNET D2 Max Iterations= 20
UNET D2 Equation= 0
UNET D2 RampUpFraction=0.1
UNET D2 TimeSlices= 1
UNET D2 BCVolumeCheck=0
UNET D1D2 MaxIter= 0
UNET D1D2 ZTol=0.01
UNET D1D2 QTol=0.1
UNET D1D2 MinQTol=1
DSS File=dss
Write IC File= 0
Write IC File at Fixed DateTime=0
Write IC File at Sim End=0
Echo Input=False
Echo Parameters=False
Echo Output=False
Write Detailed= 0
HDF Write Warmup=0
HDF Write Time Slices=0
HDF Flush=0
HDF Face Node Velocities=0
HDF Compression= 1
HDF Chunk Size= 1
HDF Spatial Parts= 1
HDF Use Max Rows=0
HDF Fixed Rows= 1
Calibration Method= 0
Calibration Iterations= 20
Calibration Max Change=0.05
Calibration Tolerance=0.2
Calibration Maximum=1.5
Calibration Minimum=0.5
Calibration Optimization Method= 1
WQ AD Non Conservative
WQ ULTIMATE=-1
WQ Max Comp Step=1HOUR
WQ Output Interval=15MIN
WQ Output Selected Increments= 0
WQ Output face flow=0
WQ Output face velocity=0
WQ Output face area=0
WQ Output face dispersion=0
WQ Output cell volume=0
WQ Output cell surface area=0
WQ Output cell continuity=0
WQ Output cumulative cell continuity=0
WQ Output face conc=0
WQ Output face dconc_dx=0
WQ Output face courant=0
WQ Output face peclet=0
WQ Output face adv mass=0
WQ Output face disp mass=0
WQ Output cell mass=0
WQ Output cell source sink temp=0
WQ Output nsm pathways=0
WQ Output nsm derived pathways=0
WQ Output MaxMinRange=-1
WQ Daily Max Min Mean=-1
WQ Daily Range=0
WQ Daily Time=0
WQ Create Restart=0
WQ Fixed Restart=0
WQ System Summary=0
WQ Write To DSS=0
WQ Use Fixed Temperature=0
Sorting and Armoring Iterations= 10
XS Update Threshold= 0.02
Bed Roughness Predictor= 0
Hydraulics Update Threshold= 0.02
Energy Slope Method= 1
Volume Change Method= 1
Sediment Retention Method= 0
XS Weighting Method= 0
Number of US Weighted Cross Sections= 1
Number of DS Weighted Cross Sections= 1
Upstream XS Weight=0
Main XS Weight=1
Downstream XS Weight=0
Number of DS XS's Weighted with US Boundary= 1
Upstream Boundary Weight= 1
Weight of XSs Associated with US Boundary= 0
Number of US XS's Weighted with DS Boundary= 1
Downstream Boundary Weight= 0.5
Weight of XSs Associated with DS Boundary= 0.5
Percentile Method= 0
Sediment Output Level= 3
Mass or Volume Output= 0
Output Increment Type= 1
Profile and TS Output Increment= 1
XS Output Flag= 0
XS Output Increment= 10
Write Gradation File= 0
Read Gradation Hotstart= 0
Write HDF5 File= 1
Write Binary Output= 1
Write DSS Sediment File= 0
SV Curve= 0
Specific Gage Flag= 0

--- SHAFTRN.f01 (steady flow) ---

Flow Title=Flows
Program Version=5.07
Number of Profiles= 6
Profile Names=P100yr,P10yr,P25yr,P50yr,P500yr,P101yr
River Rch & RM=SHAFTRN,Main            ,8319
     577     270     381     476     846     702
River Rch & RM=SHAFTRN,Main            ,6367
     641     299     423     529     941     780
Boundary for River Rch & Prof#=SHAFTRN,Main            , 1
Up Type= 0
Dn Type= 3
Dn Slope=0.10523
Boundary for River Rch & Prof#=SHAFTRN,Main            , 2
Up Type= 0
Dn Type= 3
Dn Slope=0.10523
Boundary for River Rch & Prof#=SHAFTRN,Main            , 3
Up Type= 0
Dn Type= 3
Dn Slope=0.10523
Boundary for River Rch & Prof#=SHAFTRN,Main            , 4
Up Type= 0
Dn Type= 3
Dn Slope=0.10523
Boundary for River Rch & Prof#=SHAFTRN,Main            , 5
Up Type= 0
Dn Type= 3
Dn Slope=0.10523
Boundary for River Rch & Prof#=SHAFTRN,Main            , 6
Up Type= 0
Dn Type= 3
Dn Slope=0.10523
DSS Import GetInterval= 0
DSS Import GetPeak= 0
DSS Import FillOption= 0

--- SHAFTRN.g01 (geometry) ---

Geom Title=Geometry
Program Version=5.07

River Reach=SHAFTRN         ,Main
Reach XY= 30
2440607.51899999698105.7489999982441256.43900001697874.685000002
     2441463.947 698002.05400002     2441898.787697925.987000018
2442135.56100002697988.171000019     2442374.292697811.780000016
     2442419.204697728.5110000222442718.32000002697635.078999996
2442703.26100004697451.0240000192442783.37200001697355.253000021
2442947.47200003696950.4089999942443161.63699999696797.546000019
2443207.47799999696626.2690000092443341.83399999696472.250000015
2443697.86400002696208.3959999982443869.13800004695910.776999995
     2444014.903695773.574000001      2444136.84695725.959999993
2444528.65000004695736.4459999952445023.84300002695620.523000017
     2445143.382695697.9710000012445376.15700004695648.592000008
2445513.05899999695688.7849999962445587.23500001 695588.57600002
2445897.90799999695440.0010000172446024.30300003695305.743000016
2446200.77200004695299.280000001     2446758.301694984.411000013
     2446834.544694840.7840000092446852.24345014694644.526067644

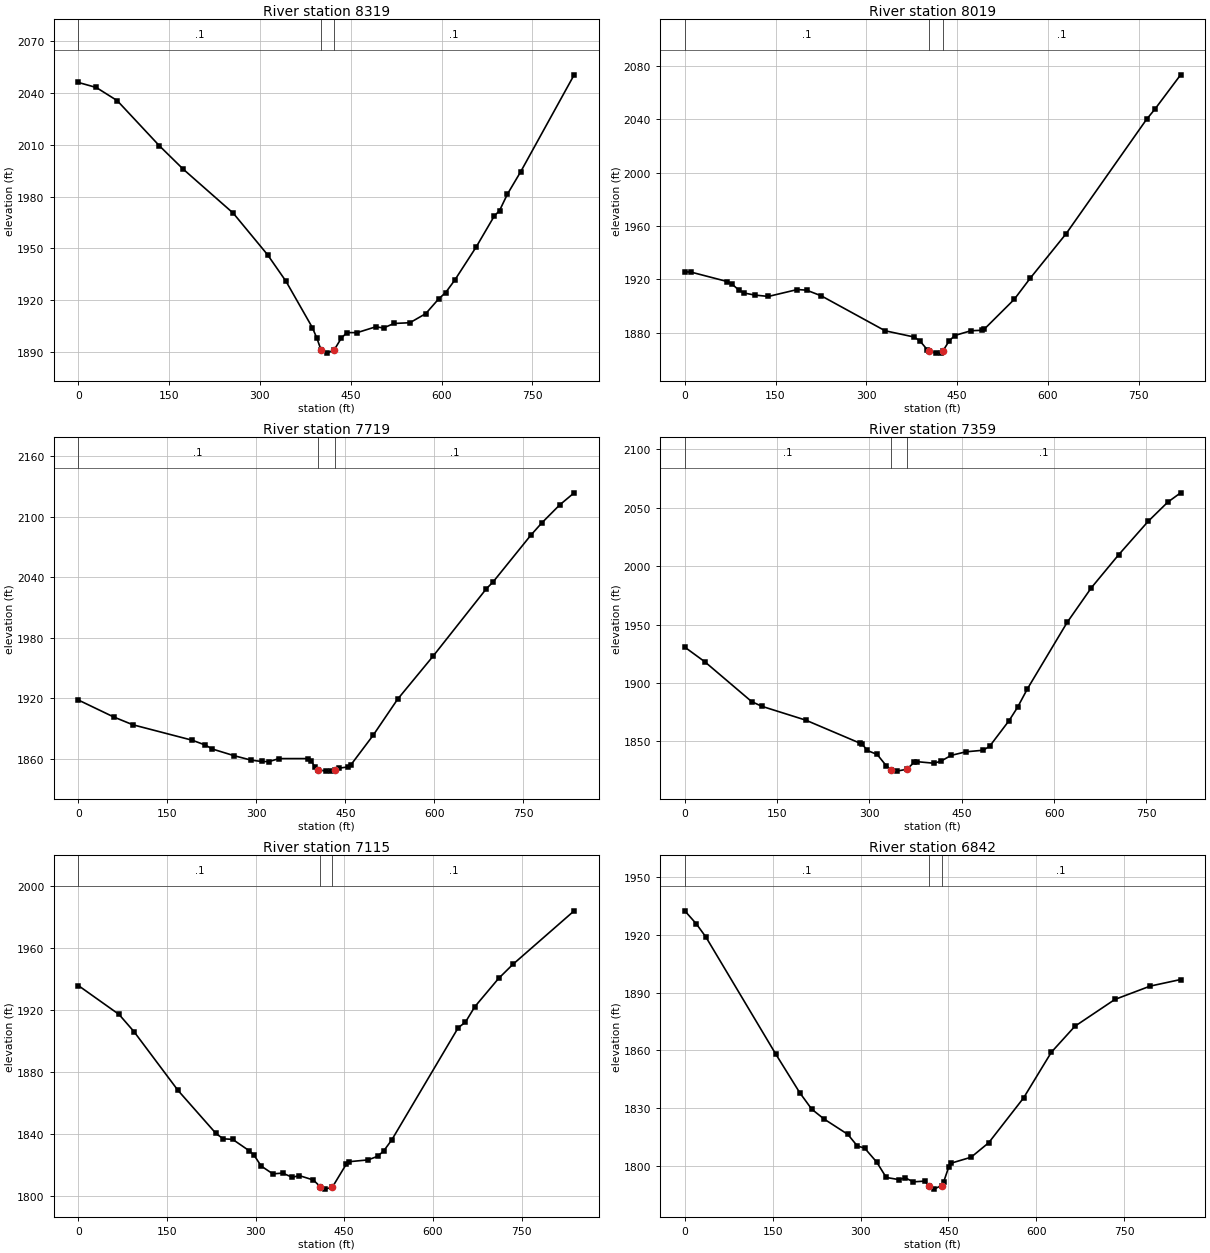
Type RM Length L Ch R = 1 ,8319    ,300,300,298.4
XS GIS Cut Line= 3
     2440778.702      698477.887     2440616.703      698101.793
     2440454.705      697725.699
#Sta/Elev= 30
       0 2045.97    29.6 2043.07    64.2 2035.46   133.9 2009.34   173.1 1995.88
   255.9 1970.38   312.5 1946.39     343 1931.01   386.5 1904.28   394.2 1897.97
     401 1891.17   410.2 1889.47   422.3 1891.13   434.4 1898.14   443.6 1901.34
   460.6 1901.32   491.1 1904.67   504.1 1904.04   521.5 1906.62   547.7 1907.05
   573.8 1912.29   595.8 1921.05   606.6 1924.42   621.7 1931.64   657.1  1950.8
     687  1968.7   695.8 1971.92   708.8 1981.43   730.6  1994.3     819 2050.38
#Mann= 3 ,-1 , 0
       0      .1       0     401    .045       0   422.3      .1       0
Bank Sta=401,422.3
XS Rating Curve= 0 ,0
Exp/Cntr=0.3,0.1

Type RM Length L Ch R = 1 ,8019    ,297.6,300,303.3
XS GIS Cut Line= 3
     2441063.942      698364.176     2440894.183      697991.168
     2440711.295       697624.84
#Sta/Elev= 30
       0 1925.67    10.9  1925.3    70.5 1918.25    77.4 1916.64    89.8 1911.66
    98.5 1909.64   115.7 1908.15   138.1 1907.13     186  1912.3   201.2 1911.83
   225.4  1907.6     331 1881.37   379.4 1876.65   389.2 1873.39   400.5 1867.25
   403.4 1866.42   414.6 1864.61   423.5 1864.97   426.5  1866.2   436.4 1873.49
   445.9  1877.8   472.7 1881.39   490.6 1881.74   495.1  1882.7   544.3 1904.91
   570.6 1920.68   630.3 1954.28   763.3 2040.11   776.4 2047.31   819.3 2073.31
#Mann= 3 ,-1 , 0
       0      .1       0   403.4    .045       0   426.5      .1       0
Bank Sta=403.4,426.5
XS Rating Curve= 0 ,0
Exp/Cntr=0.3,0.1

Type RM Length L Ch R = 1 ,7719    ,346.9,360.8,360.8
XS GIS Cut Line= 3
 2441284.9957211698302.9486142942441120.08350126697750.633094466
2441006.92086064      697517.195
#Sta/Elev= 30
       0 1918.34    59.7 1901.49    91.9 1893.78   192.1 1878.43     214 1873.68
   225.5  1869.8   263.1 1863.02   291.2 1858.71     309 1857.36   321.5 1857.26
   338.2 1860.23   387.6 1860.24   392.5 1857.87   399.3 1851.48   403.7 1849.17
   417.5  1847.8   425.9 1847.81   432.81849.165     439 1850.69   455.1 1852.02
   459.3  1853.9   496.9  1883.3   538.3 1919.21   597.8 1961.68     688 2028.85
   698.7 2035.13   762.8 2081.83   781.2 2093.96   811.7 2111.99   835.8 2123.83
#Mann= 3 ,-1 , 0
       0      .1       0   403.7    .045       0   432.8      .1       0
Bank Sta=403.7,432.8
XS Rating Curve= 0 ,0
Exp/Cntr=0.3,0.1

Type RM Length L Ch R = 1 ,7359    ,244.9,243.5,239.6
XS GIS Cut Line= 2
2441463.83706177698347.3572732272441483.91327872697542.050091076
#Sta/Elev= 30
       0  1930.6    32.5 1918.09   108.5 1884.01   124.7 1880.01   196.5 1868.08
   284.6 1848.34   288.6 1847.26   296.6 1842.07   312.6 1838.64   327.3 1829.01
   335.1 1825.61   344.6 1824.38   360.6 1825.98   372.6 1831.82   376.6 1832.52
   404.6 1831.15   416.1 1832.89   432.7 1837.86   456.6 1840.92   484.6 1842.27
   495.2 1845.61   526.9 1867.67   540.6 1879.02   556.6 1894.85   621.2  1951.8
   660.7 1981.62   704.7 2009.66   752.8  2038.4   784.7 2054.86   805.6 2062.86
#Mann= 3 ,-1 , 0
       0      .1       0   335.1    .045       0   360.6      .1       0
Bank Sta=335.1,360.6
XS Rating Curve= 0 ,0
Exp/Cntr=0.3,0.1

Type RM Length L Ch R = 1 ,7115    ,268.6,273.3,278.5
XS GIS Cut Line= 2
     2441745.987      698354.8562441665.64914092697519.649448329
#Sta/Elev= 30
       0 1935.65    68.9 1917.03    94.2 1905.96   168.7 1868.09     233 1840.35
   245.1 1836.93   261.2 1836.56   289.3  1829.2   297.3 1826.44   309.4  1819.4
   329.2 1814.34   345.6 1814.85   362.2 1812.12   373.7 1813.26   397.8 1810.39
   409.8 1805.91   417.9 1804.52   429.9 1805.79   453.8 1820.82   458.1 1822.18
   490.2 1823.34   506.3 1825.63   516.6 1829.03   530.4  1836.2   642.9  1908.5
     655 1912.02     671 1922.02   711.2 1940.21   735.3 1949.25   839.1 1983.77
#Mann= 3 ,-1 , 0
       0      .1       0   409.8    .045       0   429.9      .1       0
Bank Sta=409.8,429.9
XS Rating Curve= 0 ,0
Exp/Cntr=0.3,0.1

Type RM Length L Ch R = 1 ,6842    ,139.5,128.8,128.5
XS GIS Cut Line= 3
     2441877.758      698358.2182442003.92553288697800.168063145
       2441980.2      697527.148
#Sta/Elev= 30
       0 1932.51    19.8 1925.69    36.2  1918.8   155.1 1858.16   196.2 1838.01
   216.7 1829.45   237.7 1824.35   278.2 1816.38   294.5 1810.33   306.9 1809.24
   327.4 1802.02   343.8 1793.99   364.8 1792.91   376.6 1793.73   389.9 1791.71
   409.4 1792.09   416.4 1789.71     425 1787.93   438.4 1789.79   441.8 1791.71
   450.4 1799.38   455.1 1801.47   488.6  1804.5   518.7 1812.04   578.1 1835.28
   625.6 1859.06   665.8 1872.55     734 1886.47   794.2  1893.4   846.2 1896.82
#Mann= 3 ,-1 , 0
       0      .1       0   416.4    .045       0   438.4      .1       0
Bank Sta=416.4,438.4
XS Rating Curve= 0 ,0
Exp/Cntr=0.3,0.1

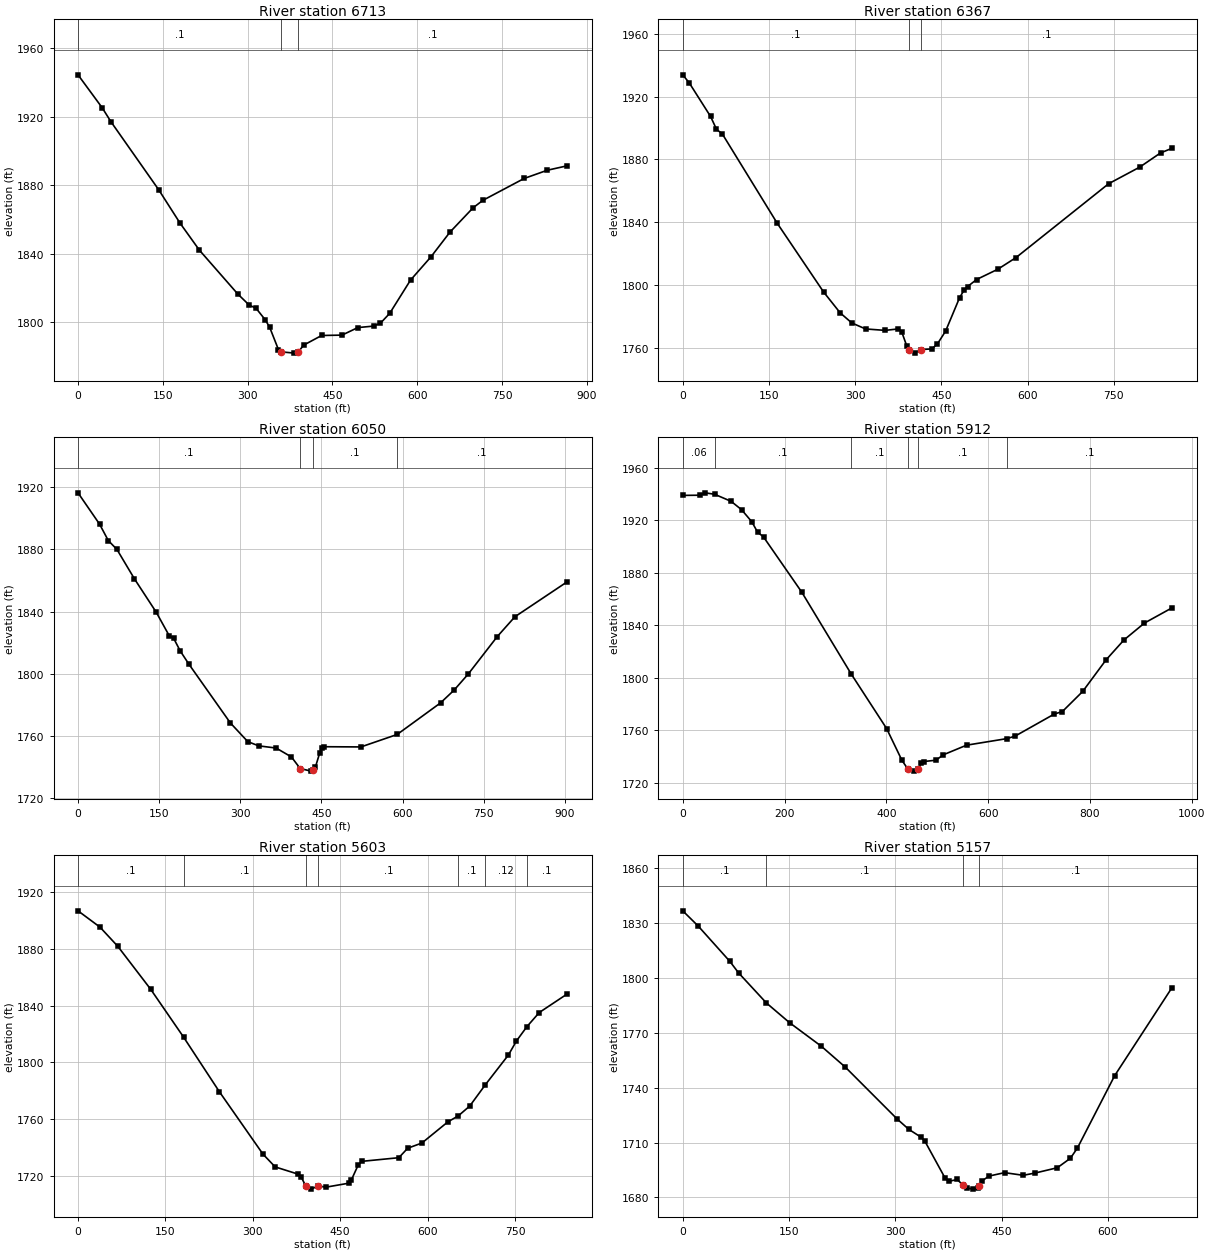
Type RM Length L Ch R = 1 ,6713    ,362.5,345.5,337.4
XS GIS Cut Line= 3
2442071.15686586 698385.48758925 2442088.4053054697846.580378992
     2442017.291       697528.32
#Sta/Elev= 30
       0 1944.49    42.6 1925.31    58.6  1916.9   142.7  1877.3   180.5 1857.76
   214.7 1841.98   282.7  1816.3   302.8 1809.87   314.8 1808.04   330.8 1801.41
   338.8 1797.01   354.5  1783.8   358.9 1782.56   382.8  1781.8   389.91782.598
   398.8 1786.43   430.8 1792.11   466.8 1792.33   494.8 1796.73   522.9 1797.61
   534.9 1799.33   551.2 1805.05     588 1824.49   624.1 1838.07   657.7 1852.51
   698.7 1866.78     716 1871.13   788.9  1883.9   829.9 1888.72   865.3 1891.32
#Mann= 3 ,-1 , 0
       0      .1       0   358.9    .045       0   389.9      .1       0
Bank Sta=358.9,389.9
XS Rating Curve= 0 ,0
Exp/Cntr=0.3,0.1

Type RM Length L Ch R = 1 ,6367    ,308.2,317.3,323.9
XS GIS Cut Line= 3
     2442589.506      698155.797 2442241.2921477697631.343959803
2442044.96637317697528.507626829
#Sta/Elev= 30
       0 1933.91    11.3 1928.79    48.4 1907.39    58.7 1899.23      69 1896.16
   164.2 1839.43     245 1795.56   273.9 1782.24   294.1 1775.81     318    1772
   352.1 1771.08   374.9 1772.02     381 1770.07     390 1760.84   393.4 1758.47
   403.7 1756.59     414  1758.9   433.2 1759.25   442.8 1762.34   457.2 1770.57
   481.6 1791.93   489.5  1796.8   495.6 1799.02   511.2  1803.5     548 1810.02
   579.8 1817.48   740.8 1864.51     795 1875.12   831.1 1884.14   851.2 1887.12
#Mann= 3 ,-1 , 0
       0      .1       0   393.4    .045       0     414      .1       0
Bank Sta=393.4,414
XS Rating Curve= 0 ,0
Exp/Cntr=0.3,0.1

Type RM Length L Ch R = 1 ,6050    ,150.4,137.9,123.9
XS GIS Cut Line= 3
2442655.73300916698078.4669070932442592.24417901697564.827866526
2442259.35691442697367.266540958
#Sta/Elev= 30
       0 1916.37    39.9 1896.22      56 1885.68      72 1879.96   104.4 1861.03
   144.7 1839.58   168.5  1824.6   176.9  1822.8     189 1814.71   205.1 1806.18
   281.7 1768.44   313.9 1756.43   334.1 1753.72   366.3 1752.32   394.6 1746.58
   410.7 1739.16   430.8 1737.48   434.9 1737.91   438.9 1740.09     447 1749.39
     451 1752.29     455 1753.17     523 1753.03  589.971761.042   670.3 1781.37
   695.2 1789.53   721.5 1799.93   775.1 1823.99   807.7 1836.71   904.6 1859.24
#Mann= 4 ,-1 , 0
       0      .1       0   410.7    .045       0   434.9      .1       0
  589.97      .1       0
Bank Sta=410.7,434.9
XS Rating Curve= 0 ,0
Exp/Cntr=0.3,0.1

Type RM Length L Ch R = 1 ,5912    ,310.3,309.1,305.7
XS GIS Cut Line= 2
2443103.58717849697869.6369890092442298.09918581697344.529814185
#Sta/Elev= 30
       0 1938.85    34.4    1939      44 1940.81   62.471939.732    95.1 1934.32
   115.6 1927.97   135.6 1918.83   147.1 1910.86   158.7 1907.23   233.8 1865.23
  331.061802.855   400.6 1761.34   430.7 1737.14     442  1730.7   454.6 1728.91
   462.2 1730.51   468.9 1735.15   473.7 1736.22   497.6 1737.23   511.9 1741.32
   557.6 1748.66  637.171753.683     653 1755.55   730.2  1772.4   745.9 1774.25
   785.9 1789.58   831.8 1813.63   866.9 1828.75   907.3 1841.67   961.5 1853.25
#Mann= 6 ,-1 , 0
       0     .06       0   62.47      .1       0  331.06      .1       0
     442    .045       0   462.2      .1       0  637.17      .1       0
Bank Sta=442,462.2
XS Rating Curve= 0 ,0
Exp/Cntr=0.3,0.1

Type RM Length L Ch R = 1 ,5603    ,437.6,446.2,450.5
XS GIS Cut Line= 2
 2443153.3573541697512.261347553 2442382.5703541697178.742347553
#Sta/Elev= 30
       0 1906.57    37.7 1895.11    68.2 1881.67   124.7 1851.45  181.051817.891
   242.6 1779.44   317.4 1735.58   338.4 1726.58   377.7 1721.51   383.3 1719.24
   390.7 1713.31   399.5 1710.97   412.5  1713.1   425.9 1712.37   464.8 1715.15
   469.2 1717.45   480.6 1727.69   486.7 1730.48   550.6 1733.06   565.8  1739.7
   590.2 1743.38   634.8 1758.24  652.641762.461   672.3 1769.36  699.241784.414
   738.7 1805.25   752.5 1815.13  770.531825.221   791.7 1835.11   839.8  1848.2
#Mann= 7 ,-1 , 0
       0      .1       0  181.05      .1       0   390.7    .045       0
   412.5      .1       0  652.64      .1       0  699.24     .12       0
  770.53      .1       0
Bank Sta=390.7,412.5
XS Rating Curve= 0 ,0
Exp/Cntr=0.3,0.1

Type RM Length L Ch R = 1 ,5157    ,65.4,66,66.7
XS GIS Cut Line= 2
2443226.86692908697250.2624750052442741.96783128696758.674644678
#Sta/Elev= 30
       0 1836.77    21.6 1828.53    66.5 1809.11    78.8 1802.82  118.041786.372
   150.8 1775.56   195.8 1762.62   229.5 1751.24   302.5 1722.91   319.1  1717.2
   336.2 1712.97   341.9  1710.6   370.4 1690.44   376.1 1688.86   387.5  1689.8
   395.6 1686.58   401.3 1685.09   410.3 1684.53     416 1684.93   418.3 1686.22
   421.7 1688.89   432.4 1691.69   454.2 1693.54   480.5 1692.09   497.5 1693.36
   528.6 1696.23     547  1701.4   556.9 1706.98   609.6 1746.66   690.5 1794.82
#Mann= 4 ,-1 , 0
       0      .1       0  118.04      .1       0   395.6    .045       0
   418.3      .1       0
Bank Sta=395.6,418.3
XS Rating Curve= 0 ,0
Exp/Cntr=0.5,0.3

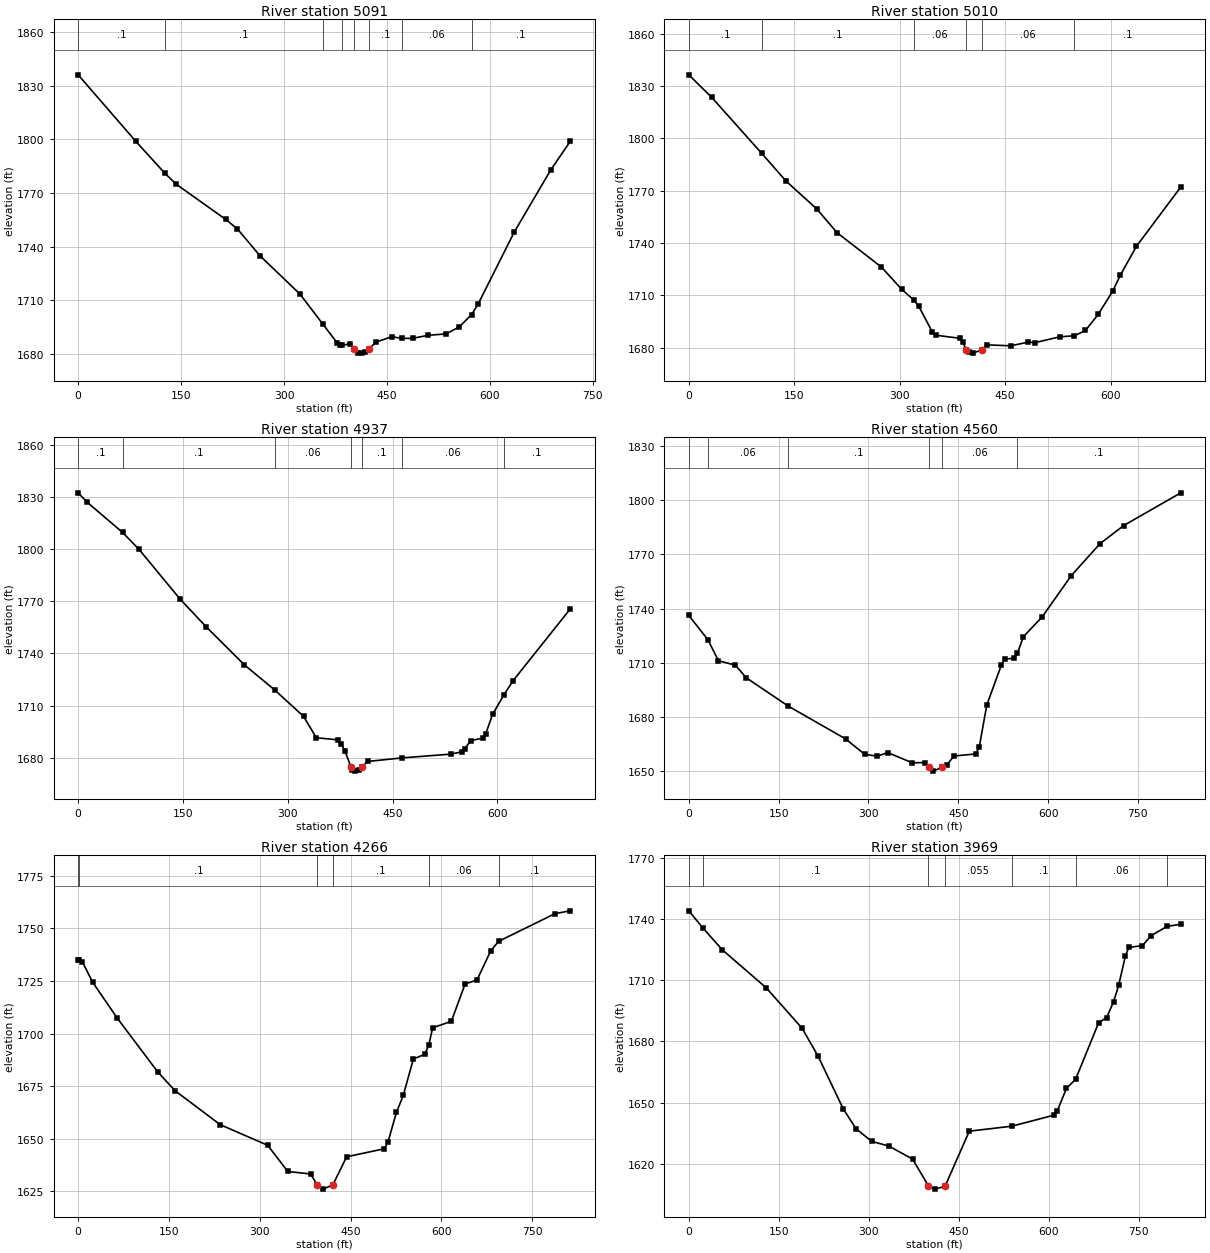
Type RM Length L Ch R = 1 ,5091    ,79.3,81.2,83
XS GIS Cut Line= 2
2443257.75548163697227.2177711382442788.25223065696685.253372278
#Sta/Elev= 30
       0 1836.12      84 1798.93  126.591780.971   143.3 1774.84     215 1755.27
   232.1 1749.92     265 1734.91   323.3 1713.47  356.811696.566   377.2 1686.32
   381.5 1684.77  384.231684.812   395.6 1685.62   401.7 1682.91   407.8 1680.65
   413.2 1680.46   418.5  1681.1   423.8 1682.87   434.4 1686.67   456.7 1689.63
  471.921688.739   487.3 1688.72     510 1690.43   536.1 1691.21   555.3 1695.12
  573.271701.995   582.6 1707.72   635.5 1748.15   688.8 1782.99     717 1798.84
#Mann= 8 ,-1 , 0
       0      .1       0  126.59      .1       0  356.81     .06       0
  384.23      .1       0   401.7    .045       0   423.8      .1       0
  471.92     .06       0  573.27      .1       0
#XS Ineff= 2 , 0
          396.54 1684.79  431.71          1684.8
Permanent Ineff=
       F       F
Bank Sta=401.7,423.8
XS Rating Curve= 0 ,0
Exp/Cntr=0.5,0.3

Type RM Length L Ch R = 1 ,5010    ,73.2,73,73.1
XS GIS Cut Line= 2
2443285.10811009697209.3888395712442891.76189244696630.700831788
#Sta/Elev= 30
       0 1836.34    32.7 1823.39  103.871791.282   138.4 1775.43     182 1759.51
     211 1745.84   273.9 1726.22   302.9 1713.42  319.78 1707.41   327.1 1703.71
   346.4 1688.93   351.9 1687.12   385.1 1685.43   389.3 1683.42   394.8 1678.49
     398 1677.32   403.7  1676.9   416.9 1678.73     424 1681.63   457.7 1681.09
   481.8 1683.13     493 1682.98   527.5 1686.24  548.381686.847   564.1 1689.88
   582.3 1699.15   602.8 1712.39   613.9 1721.68   636.6 1738.11   699.7 1772.08
#Mann= 6 ,-1 , 0
       0      .1       0  103.87      .1       0  319.78     .06       0
   394.8    .045       0   416.9     .06       0  548.38      .1       0
Bank Sta=394.8,416.9
XS Rating Curve= 0 ,0
Exp/Cntr=0.5,0.3

Type RM Length L Ch R = 1 ,4937    ,379.1,376.7,374.7
XS GIS Cut Line= 2
2443351.49211306697161.5598869432442942.41634415696588.490083748
#Sta/Elev= 30
       0  1832.5    13.1 1827.02   63.551809.683    86.8 1800.08   145.8 1771.34
   183.1 1755.36   237.6 1733.53   281.91718.739   322.7  1703.7   340.8 1691.44
   372.4 1690.23   376.8 1687.87   381.7 1683.86  390.32 1674.77   392.4 1673.08
   396.4 1672.22   401.4 1672.76   406.3 1674.73   414.4 1677.79  463.811679.851
   534.1 1682.04   548.8 1683.37     553 1684.81   561.6 1689.79   579.6 1691.26
   583.2 1693.65     593 1704.87  609.421716.245   622.5 1724.35   704.1 1765.58
#Mann= 7 ,-1 , 0
       0      .1       0   63.55      .1       0   281.9     .06       0
  390.32    .045       0   406.3      .1       0  463.81     .06       0
  609.42      .1       0
Bank Sta=390.32,406.3
XS Rating Curve= 0 ,0
Exp/Cntr=0.3,0.1

Type RM Length L Ch R = 1 ,4560    ,291.5,293.7,295.3
XS GIS Cut Line= 2
     2443608.042      696798.009      2442988.85      696258.033
#Sta/Elev= 30
       0 1736.24   31.991722.753    49.5 1711.17    77.8 1708.71      96 1701.73
   166.11686.057   261.8 1667.92   293.6 1659.41     315 1658.36     332 1660.37
   373.2 1654.69   394.4 1654.85   400.3 1652.25   408.5 1650.09   422.7 1652.25
   431.2 1653.63   442.9 1658.47   479.4 1659.59   485.1  1663.6   497.7 1686.76
   521.8 1708.63   527.6 1712.17   543.1 1712.46  548.531715.172   558.8  1724.5
     590 1735.39   638.6 1758.23   686.4 1775.84   726.1 1785.95   821.6 1804.07
#Mann= 6 ,-1 , 0
       0      .1       0   31.99     .06       0   166.1      .1       0
   400.3    .045       0   422.7     .06       0  548.53      .1       0
Bank Sta=400.3,422.7
XS Rating Curve= 0 ,0
Exp/Cntr=0.3,0.1

Type RM Length L Ch R = 1 ,4266    ,298.3,296.9,291.7
XS GIS Cut Line= 2
2443784.05535698696643.429845415      2443248.61      696032.067
#Sta/Elev= 30
       0 1734.95    1.62 1734.89       7 1734.04      24 1724.38    64.5 1707.35
   131.7 1681.68     160 1672.85   234.7  1656.7   313.1  1646.9   346.3 1634.46
     384 1633.28   395.3 1627.87   404.8 1626.08   420.8 1628.16   443.5 1641.45
   505.9 1645.27     512  1648.7   525.7 1662.49   537.1 1670.66   553.7 1687.91
   572.7 1690.15  579.131694.477   585.6 1702.75   616.4 1705.79   639.1 1723.51
   658.9 1725.49   681.6 1739.37  694.631743.818   787.7 1756.97   812.7  1758.3
#Mann= 6 ,-1 , 0
       0     .06       0    1.62      .1       0   395.3    .045       0
   420.8      .1       0  579.13     .06       0  694.63      .1       0
Bank Sta=395.3,420.8
XS Rating Curve= 0 ,0
Exp/Cntr=0.3,0.1

Type RM Length L Ch R = 1 ,3969    ,157.5,154.9,150.9
XS GIS Cut Line= 3
     2444050.319      696421.652     2443739.307      696155.201
     2443424.888      695890.629
#Sta/Elev= 30
       0 1743.93   23.931735.419    55.6 1724.93   129.3  1706.2   189.1 1686.39
   215.4 1672.91   257.5 1647.03   278.6 1637.38   304.9 1631.09   333.6 1628.79
   373.3  1622.4   399.7 1609.24   410.2 1607.71   427.2 1609.02   467.8 1636.08
  538.641638.511   608.9 1643.91   614.6 1646.08   629.8 1657.08  644.971661.406
   683.4  1689.1   696.9 1691.68   708.4 1699.46   716.8  1707.4   728.1 1721.88
   733.8 1726.01   756.5 1726.91     771 1731.79  797.241736.271   820.5 1737.39
#Mann= 7 ,-1 , 0
       0     .06       0   23.93      .1       0   399.7    .045       0
   427.2    .055       0  538.64      .1       0  644.97     .06       0
  797.24      .1       0
Bank Sta=399.7,427.2
XS Rating Curve= 0 ,0
Exp/Cntr=0.3,0.1

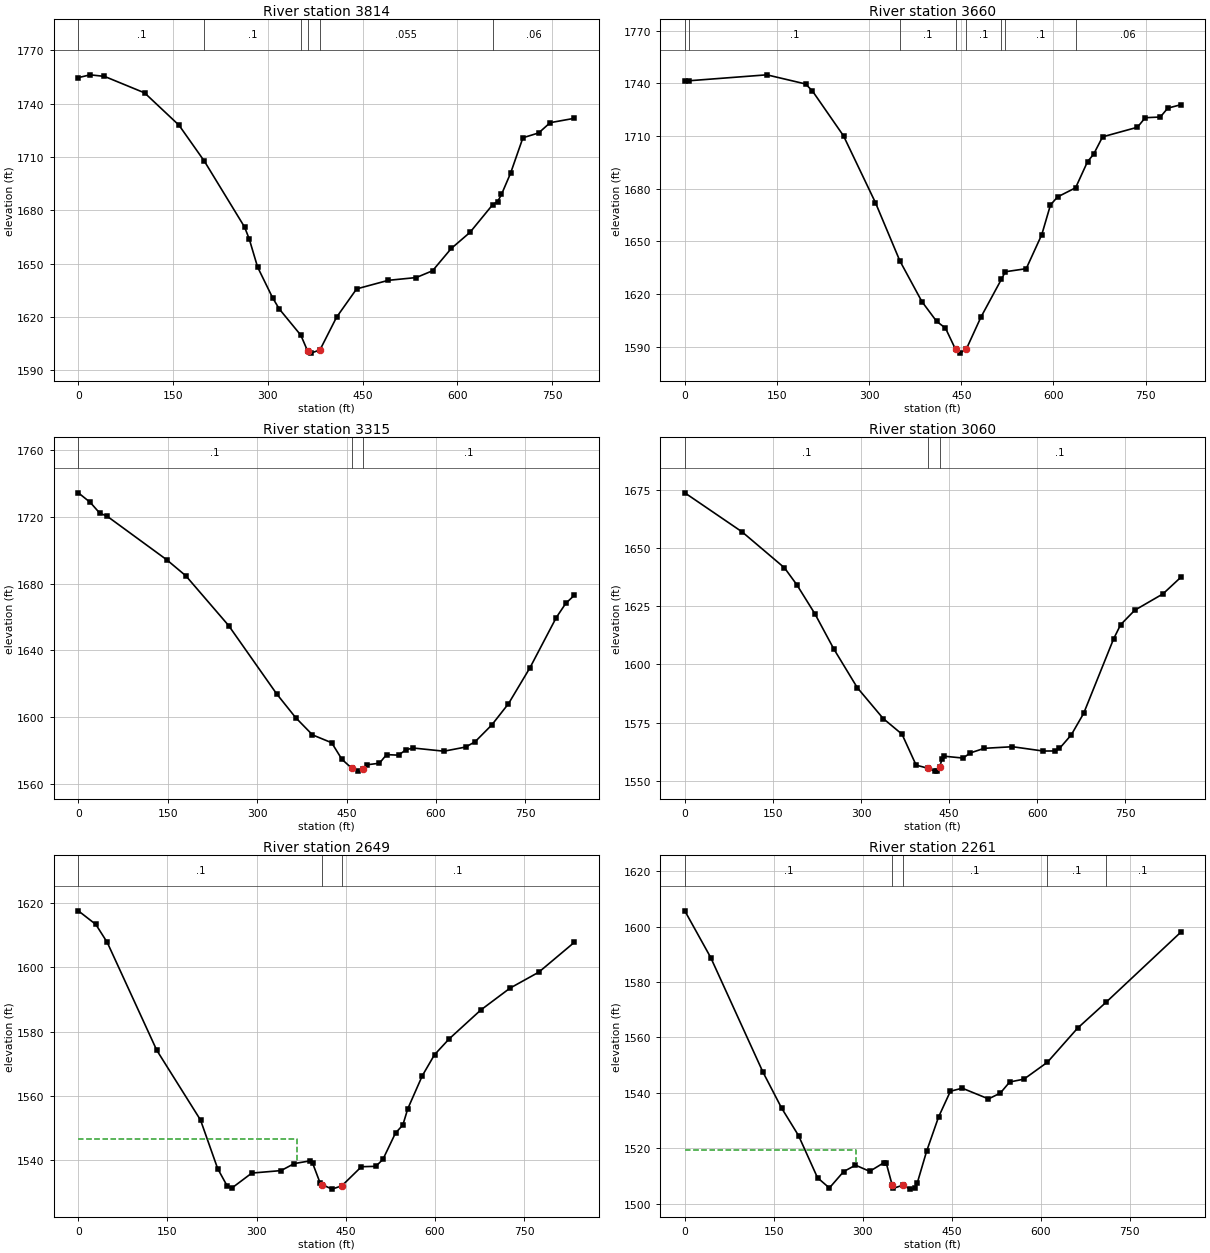
Type RM Length L Ch R = 1 ,3814    ,150,154.1,157.8
XS GIS Cut Line= 3
2444155.26479893696206.529612908 2443684.7045377695954.857014175
2443481.24508049695807.324801125
#Sta/Elev= 30
       0 1754.66    18.7 1756.24    41.4 1755.36   104.9 1746.08   159.4 1727.87
  199.611707.586   263.2 1670.54   270.6 1663.79   283.8 1648.02   307.5 1630.78
   318.1 1624.43  352.311609.628     363 1600.74     368 1599.56   382.5 1601.32
   408.8 1619.75   440.6 1635.72   490.7 1640.54     535 1642.11   560.8 1645.93
   590.4 1658.47   620.1 1667.55  655.781683.042   663.9 1684.92   669.9 1688.88
   684.3 1700.82   703.9 1720.82   728.8 1723.52     747  1729.3     785 1731.74
#Mann= 6 ,-1 , 0
       0      .1       0  199.61      .1       0  352.31    .055       0
     363    .045       0   382.5    .055       0  655.78     .06       0
Bank Sta=363,382.5
XS Rating Curve= 0 ,0
Exp/Cntr(USF)=0,0
Exp/Cntr=0.3,0.1

Type RM Length L Ch R = 1 ,3660    ,335.4,345.7,355.1
XS GIS Cut Line= 3
     2444200.411      696210.8752443754.87689065695758.565348375
2443586.31375919695724.527928292
#Sta/Elev= 30
       0 1741.13    6.781741.419   133.5  1744.8   196.5 1739.59   207.6 1735.65
   258.3 1710.03   310.2 1672.02  350.011638.788   385.8 1615.64   409.8 1604.34
   424.2  1600.5   440.71588.319   448.1 1586.24   458.4 1588.73     482  1606.8
  515.191628.274  521.631632.607   555.6 1634.35     581 1653.81   595.1 1670.69
   606.6 1675.23  635.991680.446   655.4 1695.32   665.3 1699.56   679.9 1709.47
   736.6 1714.93   749.3 1720.37   773.8 1720.76     786 1725.81   806.9 1727.74
#Mann= 8 ,-1 , 0
       0      .1       0    6.78      .1       0  350.01      .1       0
   440.7    .045       0   458.4      .1       0  515.19      .1       0
  521.63      .1       0  635.99     .06       0
Bank Sta=440.7,458.4
XS Rating Curve= 0 ,0
Exp/Cntr=0.3,0.1

Type RM Length L Ch R = 1 ,3315    ,253.6,254.5,254.8
XS GIS Cut Line= 2
2444205.27561398 696194.777638782444145.38553033695364.931997319
#Sta/Elev= 30
       0 1734.53    19.9 1728.83      36 1722.31      48 1720.59   148.3  1694.4
   180.4 1684.77   252.2 1654.95   332.7 1614.03   364.5 1599.81   392.9  1589.4
   425.1 1584.68   442.3 1574.74   458.6 1569.47   469.1 1567.66   477.1 1569.14
   485.1 1571.51   505.2 1572.38   517.2 1577.56   537.3 1577.23   549.3 1580.36
   561.3 1581.54   613.5 1579.61   649.8 1582.09   665.6 1585.22   693.7 1595.32
   721.8  1608.1   757.9 1629.69     802 1659.75     818 1668.28     832    1673
#Mann= 3 ,-1 , 0
       0      .1       0   458.6    .045       0   477.1      .1       0
Bank Sta=458.6,477.1
XS Rating Curve= 0 ,0
Exp/Cntr=0.3,0.1

Type RM Length L Ch R = 1 ,3060    ,412.2,410.9,407.6
XS GIS Cut Line= 2
     2444429.217      696148.4082444404.91380869695304.878366134
#Sta/Elev= 30
       0 1673.76    97.6 1656.96   169.6 1641.54   190.6 1634.28   221.5 1621.74
   253.6 1606.66   293.6 1590.01   337.7 1576.75   369.7 1570.02   393.7 1556.73
   413.7  1555.4   425.7 1554.15   429.7 1554.19   433.7 1555.75   437.7 1559.34
   441.7 1560.56   473.7 1559.76   485.7 1561.95   509.7 1563.95   557.7 1564.64
   609.8 1562.79   629.8 1562.82   637.7 1563.88   657.8 1569.74   678.9 1578.99
   729.8 1610.97   741.8 1617.09   765.8  1623.3   813.9 1630.34   843.9 1637.38
#Mann= 3 ,-1 , 0
       0      .1       0   413.7    .045       0   433.7      .1       0
Bank Sta=413.7,433.7
XS Rating Curve= 0 ,0
Exp/Cntr=0.3,0.1

Type RM Length L Ch R = 1 ,2649    ,380.6,388.1,390.9
XS GIS Cut Line= 2
      2444896.12      696063.675     2444712.865        695249.6
#Sta/Elev= 30
       0 1617.57    29.5 1613.33    48.7 1607.73     132 1574.22   205.6 1552.54
   234.5 1537.42   250.9 1531.89   259.1 1531.49   291.9 1536.04   341.1 1536.81
   363.3 1538.99   390.3 1539.85   394.4 1539.06   406.6 1533.09   410.8 1532.42
   426.8 1531.05   443.4 1532.07   476.4 1538.02   500.5 1538.13   512.5 1540.27
   533.8 1548.51   546.1 1550.97   554.3 1555.99   578.9 1566.32   599.4 1572.84
     624 1577.75   677.3 1586.74   726.5 1593.54   774.9  1598.5   834.4 1607.73
#Mann= 3 ,-1 , 0
       0      .1       0   410.8    .045       0   443.4      .1       0
#XS Ineff= 2 , 0
          368.46 1546.55
Permanent Ineff=
       F       F
Bank Sta=410.8,443.4
XS Rating Curve= 0 ,0
Exp/Cntr=0.3,0.1

Type RM Length L Ch R = 1 ,2261    ,395.1,390.9,384.1
XS GIS Cut Line= 2
2445153.19717588696054.5424013552445142.92617588695218.821401355
#Sta/Elev= 30
       0 1605.66    43.7 1588.81   131.7 1547.52   163.2 1534.53   191.7 1524.62
   223.7 1509.43   243.7 1505.72   267.7 1511.63   287.7 1513.95   311.7 1511.73
   335.7 1514.85   339.7 1514.58   349.5 1506.85   351.7 1505.61   367.7 1506.74
   379.7 1505.31   387.7 1505.56   391.7  1507.4   407.7 1519.03   427.7 1531.28
   447.7 1540.61   467.7  1541.7   511.9 1537.85   531.7 1539.91   547.7 1543.94
   571.7 1544.97  611.19 1551.05     662 1563.33  709.721572.607   835.8 1597.89
#Mann= 5 ,-1 , 0
       0      .1       0   349.5    .045       0   367.7      .1       0
  611.19      .1       0  709.72      .1       0
#XS Ineff= 2 , 0
           288.5 1519.37
Permanent Ineff=
       F       F
Bank Sta=349.5,367.7
XS Rating Curve= 0 ,0
Exp/Cntr=0.3,0.1

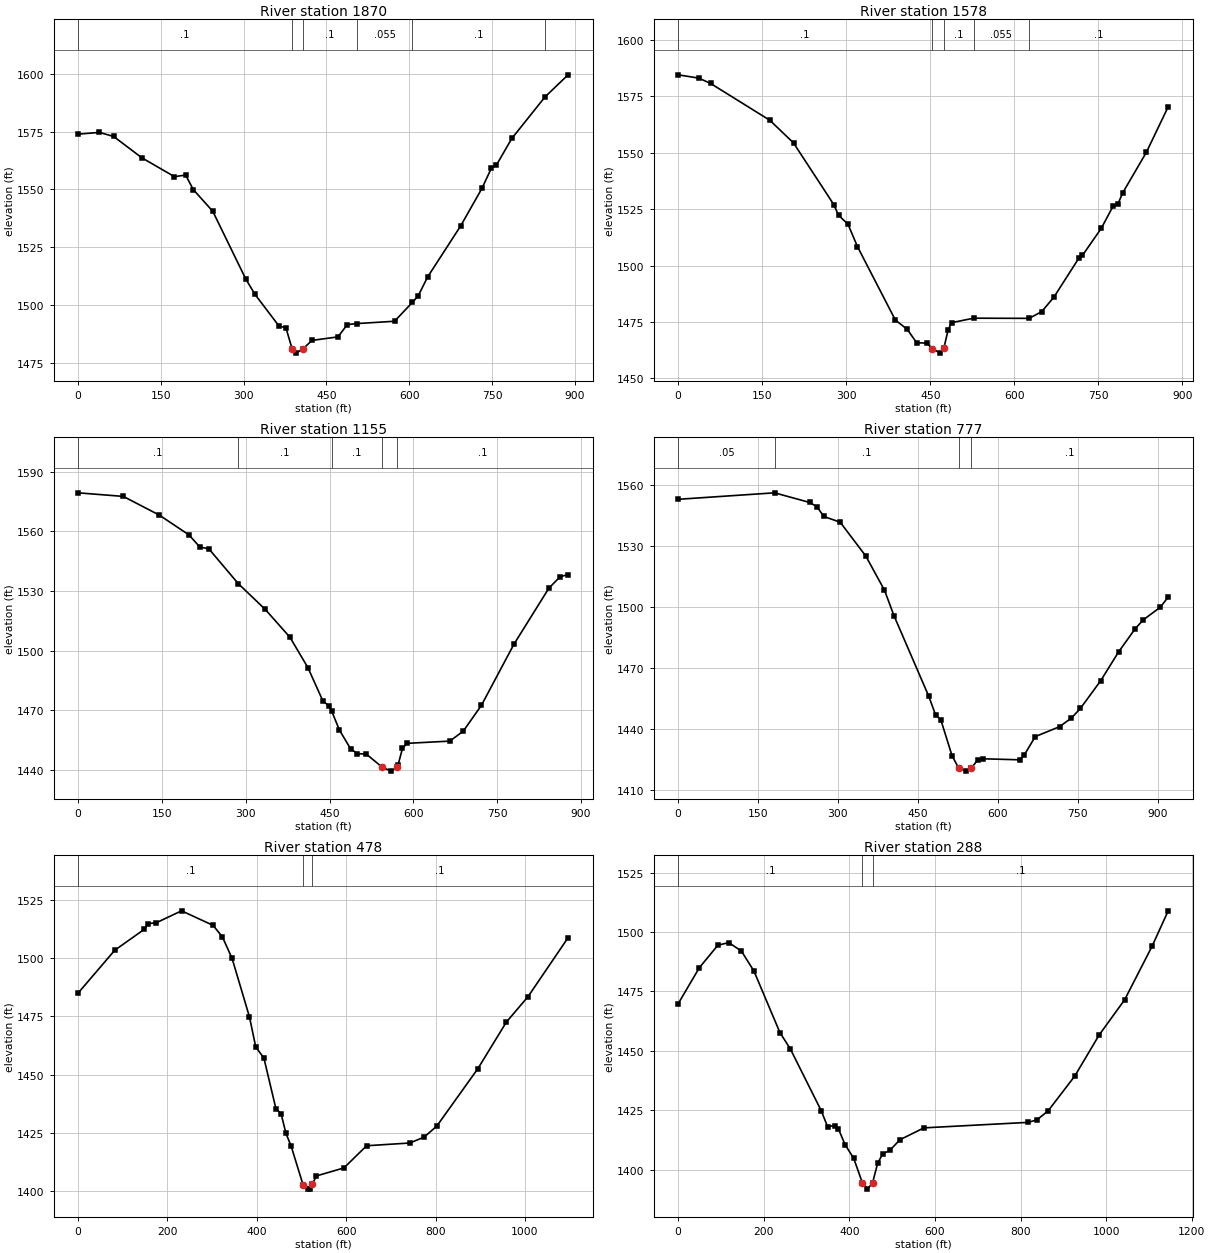
Type RM Length L Ch R = 1 ,1870    ,289.6,291.7,291.4
XS GIS Cut Line= 2
     2445651.768      696063.1412445337.40086888695232.906819681
#Sta/Elev= 30
       0 1573.93    38.8 1574.68    64.4 1572.93   115.8 1563.65   174.7 1555.52
   194.9 1556.21   208.8 1549.92   244.1 1540.51   303.9 1511.17   320.5 1504.56
   363.8  1490.9   376.7    1490     3881480.799     395 1479.09   407.4 1480.87
   423.7  1484.6   470.8 1486.12   487.9 1491.46  505.891491.901   573.4 1492.89
  605.581501.039   616.2 1503.88   633.3 1512.06   693.2 1534.19   731.7 1550.42
   748.8 1559.18     758 1560.56   785.9 1572.07  846.071590.071   887.8 1599.62
#Mann= 6 ,-1 , 0
       0      .1       0     388    .045       0   407.4      .1       0
  505.89    .055       0  605.58      .1       0  846.07      .1       0
Bank Sta=388,407.4
XS Rating Curve= 0 ,0
Exp/Cntr=0.3,0.1

Type RM Length L Ch R = 1 ,1578    ,416.9,423.4,426.8
XS GIS Cut Line= 2
 2445879.4042707695953.820944796     2445597.344      695125.962
#Sta/Elev= 30
       0 1584.48    36.9 1583.02      58 1580.65   163.7 1564.34   205.9 1554.32
   277.8 1527.01   286.2 1522.31   303.1 1518.33     320 1508.41   387.6  1475.9
   408.8 1471.76   425.7 1465.83   444.1 1465.64   453.6 1463.18   467.9 1461.22
   474.31463.469   481.9 1471.62   488.2 1474.72  527.461476.695   626.51476.617
     649 1479.63   670.8 1486.08   715.2  1503.3   721.5 1504.47   755.3 1516.54
   776.4 1526.37   784.9 1527.24   793.3 1532.15   835.6 1550.14   874.6 1570.33
#Mann= 5 ,-1 , 0
       0      .1       0   453.6    .045       0   474.3      .1       0
  527.46    .055       0   626.5      .1       0
Bank Sta=453.6,474.3
XS Rating Curve= 0 ,0
Exp/Cntr=0.3,0.1

Type RM Length L Ch R = 1 ,1155    ,382,378,371.8
XS GIS Cut Line= 2
2446137.77927893695847.1887404392446033.15010218694976.776599518
#Sta/Elev= 30
       0 1579.41    80.9 1577.61   145.3 1568.21   198.4 1558.23   217.9 1552.12
     234 1551.21  286.771533.637   334.7 1520.76     379 1506.71   411.2  1491.4
   438.2 1474.49     449 1472.13  454.031469.307   467.6 1459.95   487.8 1450.41
   499.9 1448.09     516 1447.78   544.2 1441.21   560.3 1439.25  570.25 1441.09
   572.4 1442.19   580.4 1450.71   588.5 1453.24   665.1 1454.37   689.2 1459.39
   721.5 1472.32   779.8 1503.14   842.3 1531.37   862.3 1537.12   876.7 1538.27
#Mann= 5 ,-1 , 0
       0      .1       0  286.77      .1       0  454.03      .1       0
   544.2    .045       0  570.25      .1       0
Bank Sta=544.2,570.25
XS Rating Curve= 0 ,0
Exp/Cntr=0.3,0.1

Type RM Length L Ch R = 1 ,777     ,304.6,299.3,290.9
XS GIS Cut Line= 3
2446635.23778585 695684.987836162446372.93806322695093.530948343
2446115.06197417695003.934267155
#Sta/Elev= 30
       0    1553  181.011556.183   246.9 1551.45   260.5 1549.36   273.6 1544.55
   304.2 1541.74   352.4 1525.08   387.4 1508.31   405.1 1495.87   470.5 1456.21
   483.6 1446.79     493 1444.76   514.2 1426.99   526.4 1421.01   540.5 1419.41
   550.6 1420.95   562.4 1424.94   571.9 1425.48   641.1 1424.97   649.3 1427.13
   670.5 1436.38     716 1441.25   738.3 1445.49   755.2 1450.23   793.3 1463.85
   827.2 1478.12   858.2 1489.44   873.4  1493.8   905.4 1499.99     920 1504.98
#Mann= 4 ,-1 , 0
       0     .05       0  181.01      .1       0   526.4    .045       0
   550.6      .1       0
Bank Sta=526.4,550.6
XS Rating Curve= 0 ,0
Exp/Cntr=0.3,0.1

Type RM Length L Ch R = 1 ,478     ,201.4,189.9,177.8
XS GIS Cut Line= 3
2447038.75248243695397.0402301492446553.92454161694944.400036434
2446121.40168984694972.564315154
#Sta/Elev= 30
       0 1484.94    82.1 1503.33   148.7 1512.37   157.2 1514.74   175.1 1515.12
   231.7 1520.23   302.1 1514.01   322.9 1509.12   344.8  1499.8   383.6 1474.79
   397.7 1461.86   415.9 1457.16   442.8 1435.47   454.3 1433.34   465.2 1424.92
     477 1419.33   503.5 1402.85   513.8 1400.96   519.4 1401.16   524.51403.146
   533.6 1406.62   595.2 1410.06   645.7 1419.55   742.6 1420.73   774.7 1423.28
   802.8 1427.96   894.9 1452.62   958.4  1472.5  1007.2  1483.5  1096.7 1508.72
#Mann= 3 ,-1 , 0
       0      .1       0   503.5    .045       0   524.5      .1       0
Bank Sta=503.5,524.5
XS Rating Curve= 0 ,0
Exp/Cntr(USF)=0,0
Exp/Cntr=0.3,0.1

Type RM Length L Ch R = 1 ,288     ,62.2,62.5,63.3
XS GIS Cut Line= 4
2447149.39786312695109.3622403662446999.11353626694925.109341079
2446513.13109189694910.7503657712446093.23741112 694942.38830224
#Sta/Elev= 30
       0  1469.8    49.6 1484.98    92.8 1494.42   118.1 1495.54   147.7 1491.99
   177.1 1483.55   237.8 1457.68   262.1 1450.79   334.2 1424.83   349.1 1418.09
   366.2 1418.54   374.2 1417.26   390.2 1410.44   410.2 1404.75   430.7 1394.32
   442.2 1391.79   454.2 1394.36   466.2 1402.74   478.2 1406.65   494.3 1408.05
   518.3 1412.58   574.3 1417.57   818.6 1419.89   838.7 1421.01   864.3 1424.69
   926.9 1439.41   983.7 1456.66  1043.3 1471.49  1107.4 1494.01    1145  1508.9
#Mann= 3 ,-1 , 0
       0      .1       0   430.7    .045       0   454.2      .1       0
Bank Sta=430.7,454.2
XS Rating Curve= 0 ,0
Exp/Cntr(USF)=0,0
Exp/Cntr=0.5,0.3