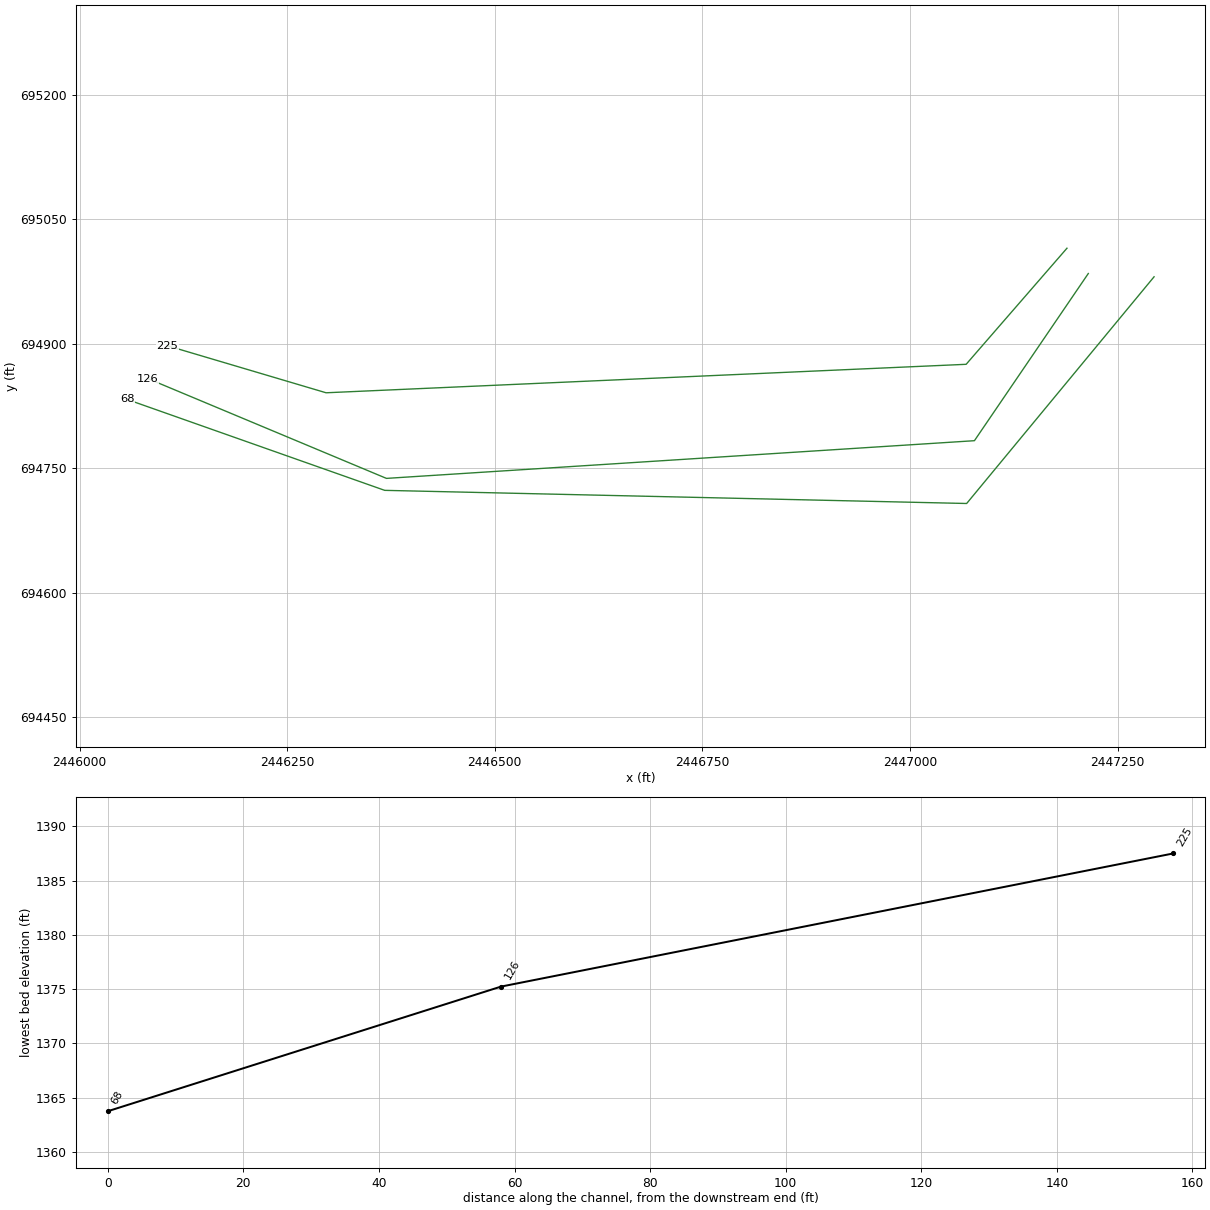
HEC-RAS study SHAFTRN.prj: SHAFTRN

--- SHAFTRN.g01 (geometry) --- (continued)

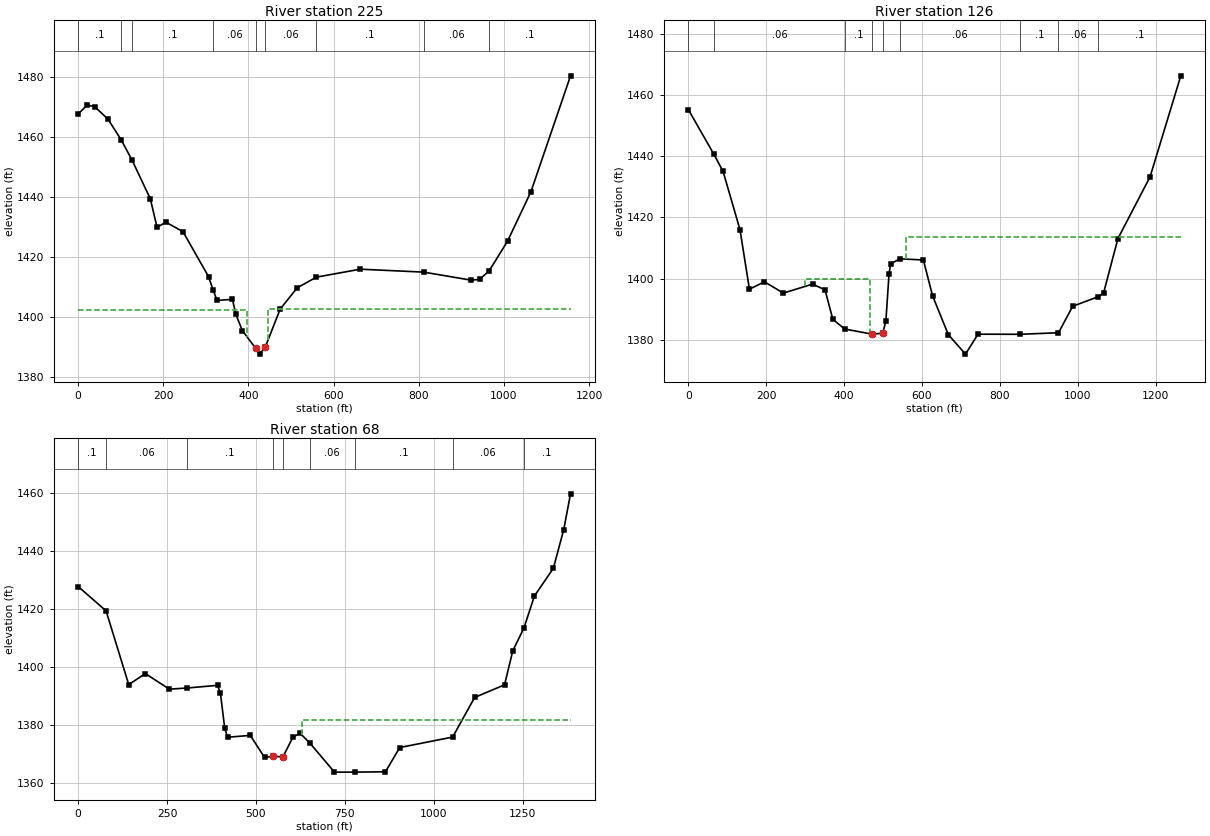
Type RM Length L Ch R = 1 ,225     ,98.3,99.2,99.6
XS GIS Cut Line= 4
2447189.11084253695014.9355924012447067.68015248694875.026319084
2446296.85925043694840.7089501582446105.47392373694897.464598767
#Sta/Elev= 30
       0 1467.59    21.2 1470.55    38.6 1470.04    69.8 1465.91  100.831459.021
  126.811452.139   169.5 1439.28   185.3  1429.8   206.2 1431.49   246.3 1428.32
   306.3 1413.33  317.241408.792   326.3  1405.4   362.4 1405.78   370.4 1400.77
   385.6 1395.36     4171389.439   426.4  1387.5   439.3 1389.78   474.5 1402.53
   514.5 1409.61  559.621413.171   662.7 1415.83   811.61414.846   923.6 1412.16
   942.9 1412.43  965.281415.262  1008.6  1425.2  1063.4 1441.63  1156.5 1480.31
#Mann= 9 ,-1 , 0
       0      .1       0  100.83     .06       0  126.81      .1       0
  317.24     .06       0     417    .045       0   439.3     .06       0
  559.62      .1       0   811.6     .06       0  965.28      .1       0
#XS Ineff= 2 , 0
          396.42  1402.3  446.23          1402.7
Permanent Ineff=
       F       F
Bank Sta=417,439.3
XS Rating Curve= 0 ,0
Exp/Cntr(USF)=0,0
Exp/Cntr=0.5,0.3

Type RM Length L Ch R = 1 ,126     ,64.4,58,60.6
XS GIS Cut Line= 4
2447214.81121101694984.4530607222447077.65571557 694782.95703884
2446369.55281856694737.5301950792446082.33803643694857.742775455
#Sta/Elev= 30
       0 1455.29   65.561440.661      89 1435.09   132.5 1415.96   156.7 1396.51
   195.4 1398.92   243.7 1395.22   318.8 1398.16   350.9 1396.28   370.9 1386.63
  401.451383.446   471.51381.787   499.11382.072   507.2 1386.09   515.2 1401.37
   519.2  1404.8  543.051406.445   603.4 1406.07   627.4 1394.24   667.5 1381.63
   711.6 1375.23   743.7 1381.76  852.071381.729  950.561382.233   987.1 1390.91
 1052.691394.043  1066.5 1395.32  1103.2 1413.07  1185.8 1433.32  1264.7 1466.39
#Mann= 9 ,-1 , 0
       0      .1       0   65.56     .06       0  401.45      .1       0
   471.5    .045       0   499.1      .1       0  543.05     .06       0
  852.07      .1       0  950.56     .06       0 1052.69      .1       0
#XS Ineff= 2 ,-1
     300     467    1400  559.14  1279.4 1413.65
Permanent Ineff=
       F       F
Bank Sta=471.5,499.1
XS Rating Curve= 0 ,0
Exp/Cntr(USF)=0,0
Exp/Cntr=0.5,0.3

Type RM Length L Ch R = 1 ,68      ,,,
XS GIS Cut Line= 4
 2447294.0051393694980.4933643082447068.30244367694707.274311699
2446367.43617828694723.1130973582446057.25995913694832.664698162
#Sta/Elev= 30
       0 1427.82   78.481419.416   142.2 1393.96   188.9 1397.77   256.3  1392.4
  305.431392.776     392 1393.71     400 1390.99     412    1379     420  1375.8
     484 1376.42     524 1368.84   547.3 1369.17     576 1369.06     604 1375.85
     624 1377.17  651.871373.715   720.7 1363.75  777.24 1363.75   864.1 1363.87
   904.1 1372.24 1052.951375.851  1114.8 1389.53  1198.9 1393.89    1222 1405.63
 1253.351413.493    1283 1424.59  1336.1 1434.11  1365.2 1447.44  1384.4 1459.82
#Mann= 9 ,-1 , 0
       0      .1       0   78.48     .06       0  305.43      .1       0
   547.3    .045       0     576      .1       0  651.87     .06       0
  777.24      .1       0 1052.95     .06       0 1253.35      .1       0
#XS Ineff= 2 , 0
                          629.57         1381.89
Permanent Ineff=
       F       F
Bank Sta=547.3,576
XS Rating Curve= 0 ,0
Exp/Cntr(USF)=0,0
Exp/Cntr=0.3,0.1
LCMann Table=0

Chan Stop Cuts=-1
Use User Specified Reach Order=0
Composite Channel Slope=5